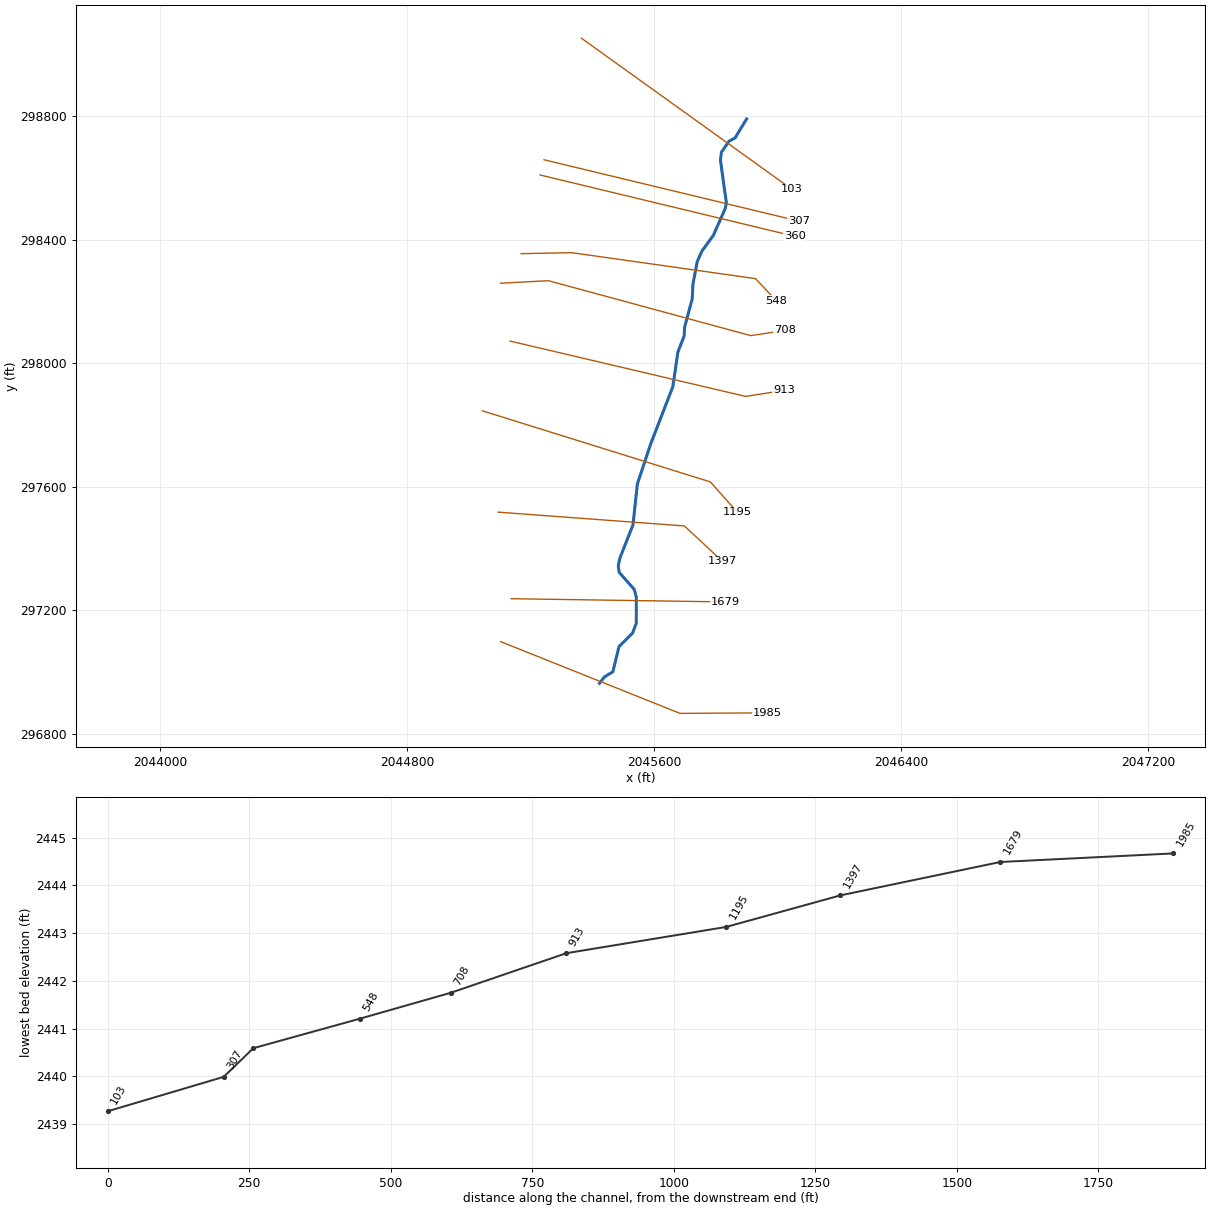
--- PATTERSNCK.prj (project) ---

Proj Title=PATTERSNCK
Current Plan=p01
Default Exp/Contr=0,0
English Units
Geom File=g01
Flow File=f01
Plan File=p01
BEGIN DESCRIPTION:
Stream Name: Patterson Creek
Flood Zone: Approximate
Summers County, West Virginia
HEC-RAS Version: 5.0.7
Hydrology Method:
regression
Model Notes:
KWSEL and shared XS pulled from final Patterson Creek Greenbrier County model
END DESCRIPTION:
DSS Export Rating Curves= 0
DSS Export Rating Curve Sorted= 0
DSS Export Volume Flow Curves= 0
DXF OffsetX= 0
DXF OffsetY= 0
DXF ScaleX= 0
DXF ScaleY= 0

--- PATTERSNCK.p01 (plan) ---

Plan Title=Floodplain
Program Version=5.07
Short Identifier=Floodplain
Geom File=g01
Flow File=f01
Subcritical Flow
K Sum by GR= 0
Std Step Tol= 0.01
Critical Tol= 0.01
Num of Std Step Trials= 20
Max Error Tol= 0.3
Flow Tol Ratio= 0.001
Split Flow NTrial= 30
Split Flow Tol= 0.02
Split Flow Ratio= 0.02
Log Output Level= 0
Friction Slope Method= 1
Unsteady Friction Slope Method= 2
Unsteady Bridges Friction Slope Method= 1
Parabolic Critical Depth
Global Vel Dist= 0 , 0 , 0
Global Log Level= 0
CheckData=True
Encroach Param=-1 ,0,0, 0
Mapping Interval=1HOUR
Computation Time Step Use Courant=        0
Computation Time Step Use Time Series=    0
Computation Time Step Count To Double=0
Computation Time Step Max Doubling=0
Computation Time Step Max Halving=0
Computation Time Step Residence Courant=0
Run HTab= 0
Run UNet= 0
Run Sediment= 0
Run PostProcess= 0
Run WQNet= 0
Run RASMapper= 0
UNET Theta= 0
UNET Theta Warmup= 0
UNET ZTol= 0
UNET ZSATol= 0
UNET MxIter= 0
UNET Max Iter WO Improvement= 0
UNET MaxInSteps= 0
UNET DtIC= 0
UNET DtMin= 0
UNET MaxCRTS= 0
UNET WFStab= 0
UNET SFStab= 0
UNET WFX= 1
UNET SFX= 1
UNET 1D Methodology=Finite Difference
UNET DSS MLevel= 1
UNET Pardiso=0
UNET DZMax Abort= 0
UNET Use Existing IB Tables= 0
UNET Froude Reduction=False
UNET Froude Limit= 0
UNET Froude Power= 0
UNET D1 Cores= 0
UNET D2 Coriolis=0
UNET D2 Cores= 0
UNET D2 Theta= 1
UNET D2 Theta Warmup= 1
UNET D2 Z Tol= 0.01
UNET D2 Volume Tol= 0.01
UNET D2 Max Iterations= 20
UNET D2 Equation= 0
UNET D2 RampUpFraction=0.1
UNET D2 TimeSlices= 1
UNET D2 BCVolumeCheck=0
UNET D1D2 MaxIter= 0
UNET D1D2 ZTol=0.01
UNET D1D2 QTol=0.1
UNET D1D2 MinQTol=1
Write IC File= 0
Write IC File at Fixed DateTime=0
Write IC File at Sim End=0
Echo Input=False
Echo Parameters=False
Echo Output=False
Write Detailed= 0
HDF Write Warmup=0
HDF Write Time Slices=0
HDF Flush=0
HDF Face Node Velocities=0
HDF Compression= 1
HDF Chunk Size= 1
HDF Spatial Parts= 1
HDF Use Max Rows=0
HDF Fixed Rows= 1
Calibration Method= 0
Calibration Iterations= 20
Calibration Max Change=0.05
Calibration Tolerance=0.2
Calibration Maximum=1.5
Calibration Minimum=0.5
Calibration Optimization Method= 1
WQ AD Non Conservative
WQ ULTIMATE=-1
WQ Max Comp Step=1HOUR
WQ Output Interval=15MIN
WQ Output Selected Increments= 0
WQ Output face flow=0
WQ Output face velocity=0
WQ Output face area=0
WQ Output face dispersion=0
WQ Output cell volume=0
WQ Output cell surface area=0
WQ Output cell continuity=0
WQ Output cumulative cell continuity=0
WQ Output face conc=0
WQ Output face dconc_dx=0
WQ Output face courant=0
WQ Output face peclet=0
WQ Output face adv mass=0
WQ Output face disp mass=0
WQ Output cell mass=0
WQ Output cell source sink temp=0
WQ Output nsm pathways=0
WQ Output nsm derived pathways=0
WQ Output MaxMinRange=-1
WQ Daily Max Min Mean=-1
WQ Daily Range=0
WQ Daily Time=0
WQ Create Restart=0
WQ Fixed Restart=0
WQ System Summary=0
WQ Write To DSS=0
WQ Use Fixed Temperature=0
Sorting and Armoring Iterations= 10
XS Update Threshold= 0.02
Bed Roughness Predictor= 0
Hydraulics Update Threshold= 0.02
Energy Slope Method= 1
Volume Change Method= 1
Sediment Retention Method= 0
XS Weighting Method= 0
Number of US Weighted Cross Sections= 1
Number of DS Weighted Cross Sections= 1
Upstream XS Weight=0
Main XS Weight=1
Downstream XS Weight=0
Number of DS XS's Weighted with US Boundary= 1
Upstream Boundary Weight= 1
Weight of XSs Associated with US Boundary= 0
Number of US XS's Weighted with DS Boundary= 1
Downstream Boundary Weight= 0.5
Weight of XSs Associated with DS Boundary= 0.5
Percentile Method= 0
Sediment Output Level= 3
Mass or Volume Output= 0
Output Increment Type= 1
Profile and TS Output Increment= 1
XS Output Flag= 0
XS Output Increment= 10
Write Gradation File= 0
Read Gradation Hotstart= 0
Write HDF5 File= 1
Write Binary Output= 1
Write DSS Sediment File= 0
SV Curve= 0
Specific Gage Flag= 0

--- PATTERSNCK.f01 (steady flow) ---

Flow Title=Flows
Program Version=5.07
Number of Profiles= 6
Profile Names=01pct,10pct,04pct,02pct,0_2pct,01plus
River Rch & RM=PATTERSNCK,Main            ,1985
     608     322     427     515     848     899
River Rch & RM=PATTERSNCK,Main            ,360
     641     340     451     543     893     948
Boundary for River Rch & Prof#=PATTERSNCK,Main            , 1
Up Type= 0
Dn Type= 1
Dn Known WS=2445
Boundary for River Rch & Prof#=PATTERSNCK,Main            , 2
Up Type= 0
Dn Type= 1
Dn Known WS=2444.4
Boundary for River Rch & Prof#=PATTERSNCK,Main            , 3
Up Type= 0
Dn Type= 1
Dn Known WS=2444.7
Boundary for River Rch & Prof#=PATTERSNCK,Main            , 4
Up Type= 0
Dn Type= 1
Dn Known WS=2444.8
Boundary for River Rch & Prof#=PATTERSNCK,Main            , 5
Up Type= 0
Dn Type= 1
Dn Known WS=2445.4
Boundary for River Rch & Prof#=PATTERSNCK,Main            , 6
Up Type= 0
Dn Type= 1
Dn Known WS=2445.5
DSS Import GetInterval= 0
DSS Import GetPeak= 0
DSS Import FillOption= 0

--- PATTERSNCK.g01 (geometry) ---

Geom Title=Geometry
Program Version=5.07

River Reach=PATTERSNCK      ,Main
Reach XY= 30
2045423.49511133296962.9657400742045439.18647121296983.868393131
2045466.74489795297000.4637438112045486.63171693297082.162438871
 2045530.7419127297126.1347902792045542.73437217297158.114682213
2045542.83086322297243.1646534322045535.74566303297267.976638552
2045487.04525001297322.9765389032045484.42620714297344.066726256
2045489.11291544297367.9138008442045531.98251195297476.259469204
2045546.07000001297608.4989999982045590.55800003      297741.963
2045661.08799998297924.2539999932045677.36399998298036.017000005
2045697.97999999298089.185000002     2045699.065298116.312000006
     2045724.022298209.6280000062045726.19200002298256.285999998
2045740.29799999298330.0700000082045755.48899998298363.707000002
2045792.38099998      298414.706     2045830.358298500.426000014
2045834.69536747298519.1822057662045815.26179342298658.871400416
2045818.58540085298684.0378306812045843.46586794 298719.95083043
2045862.53634112298730.1836607162045900.14378908298791.777151704

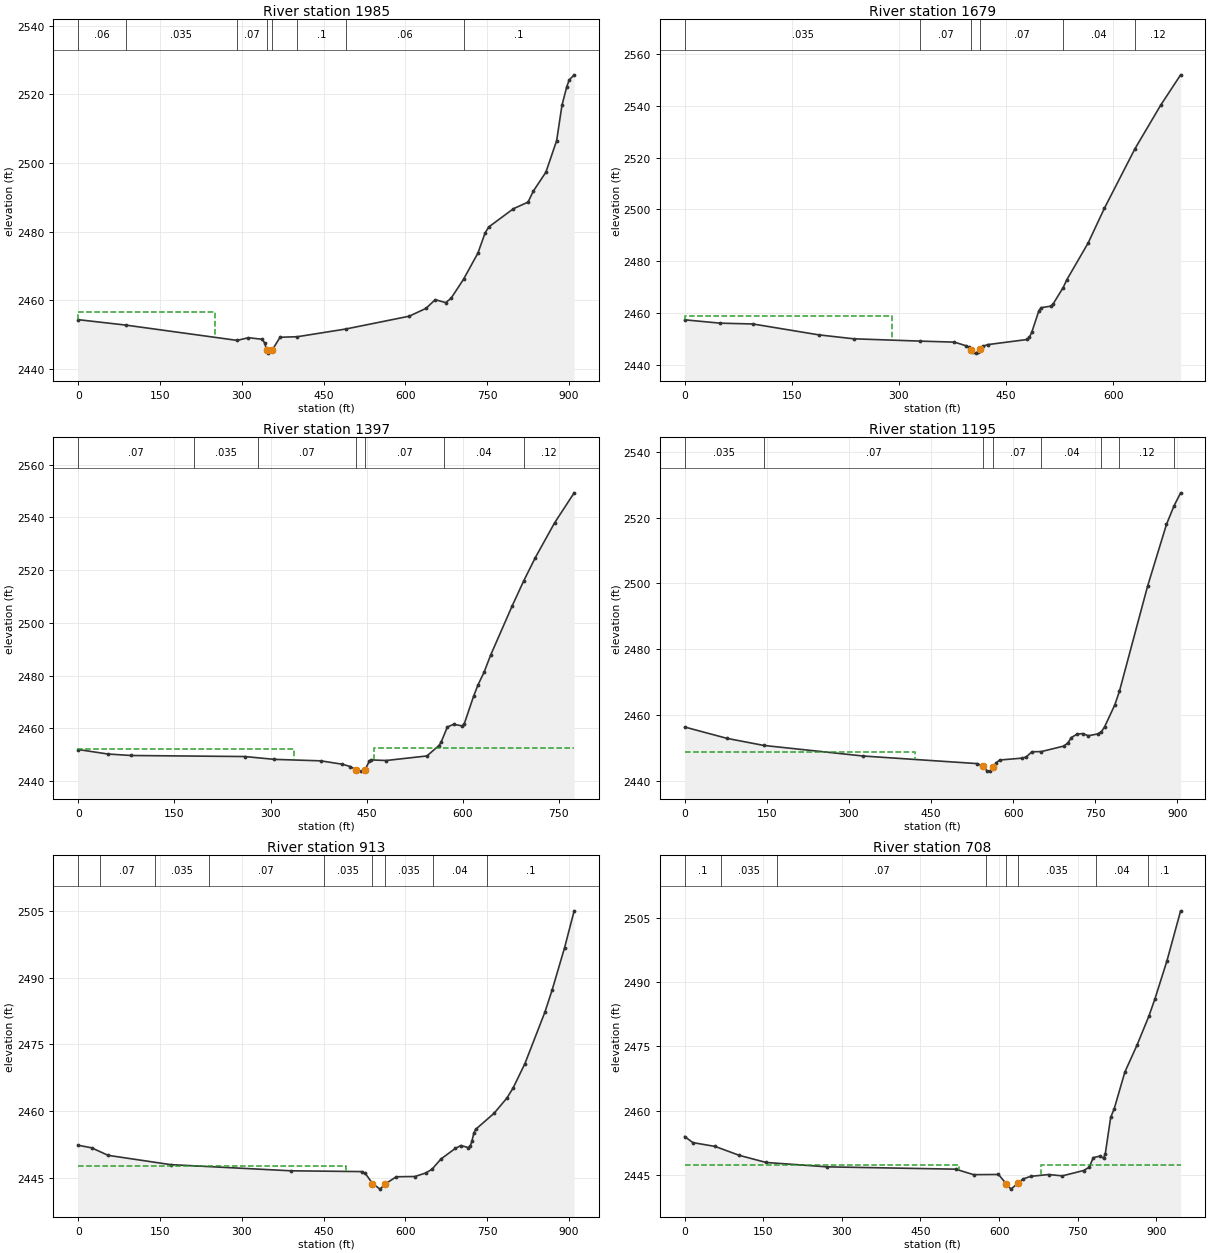
Type RM Length L Ch R = 1 ,1985    ,303.5,306,307.5
XS GIS Cut Line= 3
2045102.68714172297098.477762789 2045684.2843639296865.838873878
2045967.27047503296867.574985012
#Sta/Elev= 30
       0 2454.41      87 2452.84   291.4 2448.38   312.2 2449.16   336.9 2448.71
   341.8 2447.69   345.4 2445.69   348.9 2444.67     356 2445.63   370.1 2449.29
   401.9 2449.45   490.2 2451.68   606.9 2455.42   637.8 2457.71   654.6 2460.23
   673.9 2459.38   683.7 2460.64   706.6 2466.19     733 2473.83     746 2479.62
   752.6 2481.38   798.1 2486.73   824.8 2488.64   834.6 2491.87   857.6 2497.36
   877.3 2506.55   887.1 2516.88   895.9 2522.25   900.2 2524.19   909.4 2525.71
#Mann= 8 ,-1 , 0
       0     .06       0      87    .035       0   291.4     .07       0
   345.4    .045       0     356     .07       0   401.9      .1       0
   490.2     .06       0   706.6      .1       0
#XS Ineff= 2 , 0
       0     250 2456.67               0
Permanent Ineff=
       F       F
Bank Sta=345.4,356
XS Rating Curve= 0 ,0
Exp/Cntr(USF)=0,0
Exp/Cntr=0.3,0.1

Type RM Length L Ch R = 1 ,1679    ,282.7,282.7,280.8
XS GIS Cut Line= 2
2045137.40936393297237.3666516692045831.85380834297226.949984998
#Sta/Elev= 30
       0 2457.36    49.7 2456.07    95.7 2455.75   187.5 2451.56   236.7 2450.03
   330.1 2449.13   377.8 2448.74   393.4 2447.39   397.5 2446.85   401.5 2445.76
   404.1 2444.87   407.4 2444.49   410.7    2445   413.4 2445.91   417.2 2447.09
   424.2 2447.77   479.6 2449.76   482.8 2450.65   486.1  2452.6     496 2460.84
   499.2 2462.06   512.4 2462.64   515.6 2463.34     530 2469.83   535.3 2472.93
   564.9    2487   587.8 2500.49   630.5 2523.44   666.5 2540.27   694.5 2552.03
#Mann= 6 ,-1 , 0
       0    .035       0   330.1     .07       0   401.5    .045       0
   413.4     .07       0     530     .04       0   630.5     .12       0
#XS Ineff= 2 , 0
       0     290    2459               0
Permanent Ineff=
       F       F
Bank Sta=401.5,413.4
XS Rating Curve= 0 ,0
Exp/Cntr(USF)=0,0
Exp/Cntr=0.3,0.1

Type RM Length L Ch R = 1 ,1397    ,204,201.4,198
XS GIS Cut Line= 3
2045095.06282018 297517.887160192045698.56982684297473.090349929
 2045822.0643396297358.422032393
#Sta/Elev= 30
       0 2451.98    46.3 2450.28    82.4 2449.72   260.1 2449.32   306.2 2448.25
   378.6 2447.69   412.3 2446.39   424.7 2445.52   433.7  2444.2     441 2443.79
   447.6 2444.36   454.2 2447.61   457.5 2448.03   480.5 2447.82     544 2449.55
   562.8  2453.5   566.1 2454.73   575.9 2460.54   585.8 2461.55     599 2460.94
   602.2 2461.68   616.8 2472.18   623.6 2476.45   633.1 2481.27   643.3 2487.72
     677 2506.46   695.2 2516.04   713.1 2524.76   743.2 2537.96   773.7 2549.34
#Mann= 7 ,-1 , 0
       0     .07       0     180    .035       0     280     .07       0
   433.7    .045       0   447.6     .07       0     570     .04       0
  695.17     .12       0
#XS Ineff= 2 , 0
          336.47    2452  460.69         2452.42
Permanent Ineff=
       F       F
Bank Sta=433.7,447.6
XS Rating Curve= 0 ,0
Exp/Cntr=0.3,0.1

Type RM Length L Ch R = 1 ,1195    ,281.6,282.4,284
XS GIS Cut Line= 3
2045044.41025893297846.0244408472045782.55546947297615.865942405
 2045870.6567931297516.879417973
#Sta/Elev= 30
       0  2456.5    77.3 2453.06   144.3 2450.92     326 2447.71   534.4 2445.41
   545.1 2444.57   551.6  2443.3   557.4 2443.13   563.9 2444.25   568.9 2445.69
   575.6  2446.5   616.9 2447.08   623.8 2447.45   634.2    2449   651.2 2449.05
   692.5 2450.73   699.7 2451.67   706.2 2453.31   716.5 2454.34   726.8 2454.51
   737.2 2453.86   754.3  2454.4   761.2 2455.11   766.9 2456.57   785.6 2463.24
     794 2467.37   845.3 2499.15   879.9 2517.93   893.6  2523.5   905.7 2527.48
#Mann= 8 ,-1 , 0
       0    .035       0   144.3     .07       0   545.1    .045       0
   563.9     .07       0   651.2     .04       0   761.2      .1       0
     794     .12       0   893.6      .1       0
#XS Ineff= 2 , 0
       0     420    2449               0
Permanent Ineff=
       F       F
Bank Sta=545.1,563.9
XS Rating Curve= 0 ,0
Exp/Cntr=0.3,0.1

Type RM Length L Ch R = 1 ,913     ,204.8,204.6,203.3
XS GIS Cut Line= 3
2045133.70955264298072.1445176682045896.94093045 297892.86697181
2046021.17059915297912.208117836
#Sta/Elev= 30
       0 2452.41    24.5 2451.84    54.9 2450.15   169.5 2448.07   389.7 2446.69
   519.9 2446.51   526.7 2446.09   539.8 2443.84   553.6 2442.58   562.8 2443.71
   583.4 2445.35   617.7 2445.41   637.7 2446.21   648.9 2447.03   665.3 2449.33
   691.8 2451.71   701.9 2452.35   715.4  2451.9   718.8 2452.14   722.2 2453.32
   725.5 2455.06   728.9 2455.97   762.6 2459.55   786.2 2462.97   797.8 2465.26
   819.4 2470.72   855.9  2482.2   869.2 2487.16   892.2 2496.71   909.7 2504.95
#Mann= 9 ,-1 , 0
       0    .035       0      40     .07       0     140    .035       0
     240     .07       0     450    .035       0   539.8    .045       0
   562.8    .035       0     650     .04       0     750      .1       0
#XS Ineff= 2 , 0
          491.27 2447.83
Permanent Ineff=
       F       F
Bank Sta=539.8,562.8
XS Rating Curve= 0 ,0
Exp/Cntr(USF)=0,0
Exp/Cntr=0.3,0.1

Type RM Length L Ch R = 1 ,708     ,158,159.7,161.6
XS GIS Cut Line= 4
2045102.75380953298259.5427234972045257.84569711 298267.79300132
2045913.47913753298089.8282771652046023.94683695 298106.56580738
#Sta/Elev= 30
       0    2454    15.5 2452.59    58.2 2451.69   104.2 2449.62   155.3 2447.96
   271.8 2446.94   517.2  2446.4   551.2 2445.12   598.8 2445.16     614 2442.96
   622.6 2441.75   635.5 2443.07   645.4  2444.1     660 2444.72   694.3 2445.15
   720.6 2444.84   761.1 2446.08   771.8 2446.83   779.8 2449.09   792.5 2449.44
   799.3 2448.96   802.7 2450.03   812.9 2458.45   819.7 2460.48     840 2469.02
   863.2  2475.3   885.7    2482   897.3 2486.04   920.3 2494.91   946.4 2506.57
#Mann= 8 ,-1 , 0
       0      .1       0      70    .035       0  175.31     .07       0
  575.31    .035       0     614    .045       0   635.5    .035       0
  785.31     .04       0  884.67      .1       0
#XS Ineff= 2 , 0
          523.94 2447.39  679.44         2447.47
Permanent Ineff=
       F       F
Bank Sta=614,635.5
XS Rating Curve= 0 ,0
Exp/Cntr(USF)=0,0
Exp/Cntr=0.3,0.1

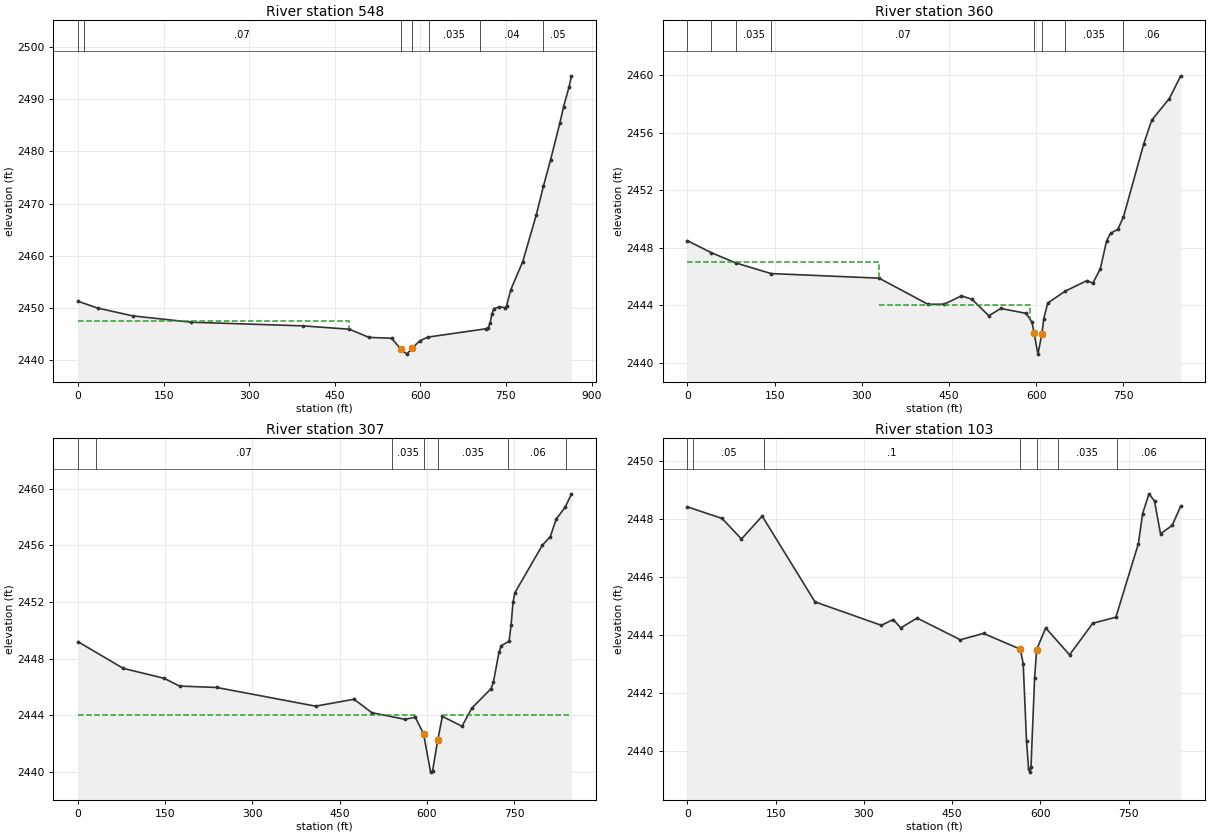
Type RM Length L Ch R = 1 ,548     ,189.1,188.8,184.5
XS GIS Cut Line= 4
2045169.43269797298355.3648242622045333.81071088298358.497495365
2045928.84071377298274.4478446642045997.12983705298202.141714135
#Sta/Elev= 30
       0 2451.32    34.1 2450.03    96.4 2448.52   198.5 2447.32     394 2446.62
   475.3 2445.98     510 2444.41   549.7 2444.25   565.3 2442.21   576.2 2441.21
   585.6 2442.37   598.5 2443.71   612.7 2444.46   715.4 2446.07   718.7 2446.24
     722 2447.09   725.3 2448.81   728.6 2449.91   738.6 2450.25   748.5  2450.1
   751.1 2450.45   758.5 2453.54   779.5 2458.94   803.2 2467.88   815.7 2473.37
   828.2 2478.39   844.5 2485.46     851 2488.57   860.7  2492.4   864.8 2494.48
#Mann= 7 ,-1 , 0
       0      .1       0      10     .07       0   565.3    .045       0
   585.6     .07       0  614.41    .035       0  704.41     .04       0
  815.34     .05       0
#XS Ineff= 2 , 0
          474.93 2447.61
Permanent Ineff=
       F       F
Bank Sta=565.3,585.6
XS Rating Curve= 0 ,0
Exp/Cntr(USF)=0,0
Exp/Cntr=0.5,0.3

Type RM Length L Ch R = 1 ,360     ,51.2,52.3,52.1
XS GIS Cut Line= 2
2045230.80867125298610.3440557892046055.92675754298411.622217128
#Sta/Elev= 30
       0 2448.49    41.4 2447.65    83.3 2446.94     144  2446.2   329.7 2445.88
   413.9 2444.06     442 2444.07   471.4 2444.65   489.6 2444.41   518.6 2443.26
   539.1 2443.77   582.7 2443.43   592.9 2442.81   596.42442.051     603 2440.59
   609.92442.013   613.1 2443.06   619.9 2444.15   650.2 2444.98   687.4 2445.71
   697.5 2445.53   710.4 2446.54   721.1 2448.47   727.9 2449.01   740.4 2449.27
   750.2 2450.15   785.2 2455.25   798.7 2456.88   829.1 2458.39   848.7 2459.97
#Mann= 8 ,-1 , 0
       0      .1       0    41.4     .07       0    83.3    .035       0
     144     .07       0   596.4    .045       0   609.9     .07       0
   650.2    .035       0   750.2     .06       0
#XS Ineff= 3 ,-1
       0     330    2447     330     589    2444     621  848.32    2444
Permanent Ineff=
       F       F       F
Bank Sta=596.4,609.9
XS Rating Curve= 0 ,0
Exp/Cntr(USF)=0,0
Exp/Cntr=0.5,0.3

Type RM Length L Ch R = 1 ,307     ,210.8,204.8,199.3
XS GIS Cut Line= 2
2045243.86786683298659.5737949512046068.98595311298460.851956289
#Sta/Elev= 30
       0  2449.2    77.7 2447.32   147.8 2446.62   174.5 2446.07   238.6 2445.97
   408.6 2444.65   474.8 2445.14   505.2 2444.19   562.6 2443.72     580 2443.87
   594.32442.698   606.4 2439.99   609.9 2440.09   618.6 2442.25   626.7 2443.93
   660.4 2443.23   677.3 2444.51   710.5 2445.89   714.4 2446.34   724.1 2448.47
   727.9 2448.92   741.4 2449.24   744.8 2450.36   748.2    2452   751.5 2452.67
   798.8 2456.03   812.3 2456.62   822.4 2457.86   838.3 2458.73   848.7 2459.65
#Mann= 7 ,-1 , 0
       0      .1       0      30     .07       0     540    .035       0
   594.3    .045       0   618.6    .035       0     740     .06       0
     840      .1       0
#XS Ineff= 2 , 0
             580    2444     630            2444
Permanent Ineff=
       F       F
Bank Sta=594.3,618.6
XS Rating Curve= 0 ,0
Exp/Cntr(USF)=0,0
Exp/Cntr=0.5,0.3

Type RM Length L Ch R = 1 ,103     ,279.7,286.2,283.8
XS GIS Cut Line= 2
2045365.50009265299053.024705925 2046046.8263973298563.963506766
#Sta/Elev= 30
       0 2448.43      59 2448.03    91.9 2447.32   127.2 2448.11   216.9 2445.15
   329.7 2444.34   349.9 2444.54   362.7 2444.25   390.5 2444.59     464 2443.84
   503.4 2444.06     5662443.514   570.9 2443.01   576.5 2440.35   580.1 2439.37
   582.2 2439.27   584.1 2439.45   590.3 2442.53   593.7  2443.5   609.1 2444.25
   649.7 2443.32   689.1 2444.41   728.4 2444.62   766.7 2447.16   773.9  2448.2
   784.7 2448.88   794.1 2448.63   804.3  2447.5   824.1 2447.79   838.7 2448.46
#Mann= 7 ,-1 , 0
       0      .1       0      10     .05       0     130      .1       0
     566    .045       0   593.7      .1       0     630    .035       0
     730     .06       0
Bank Sta=566,593.7
XS Rating Curve= 0 ,0
Exp/Cntr(USF)=0,0
Exp/Cntr=0.3,0.1
LCMann Table=0

Chan Stop Cuts=-1
Use User Specified Reach Order=0
Composite Channel Slope=5